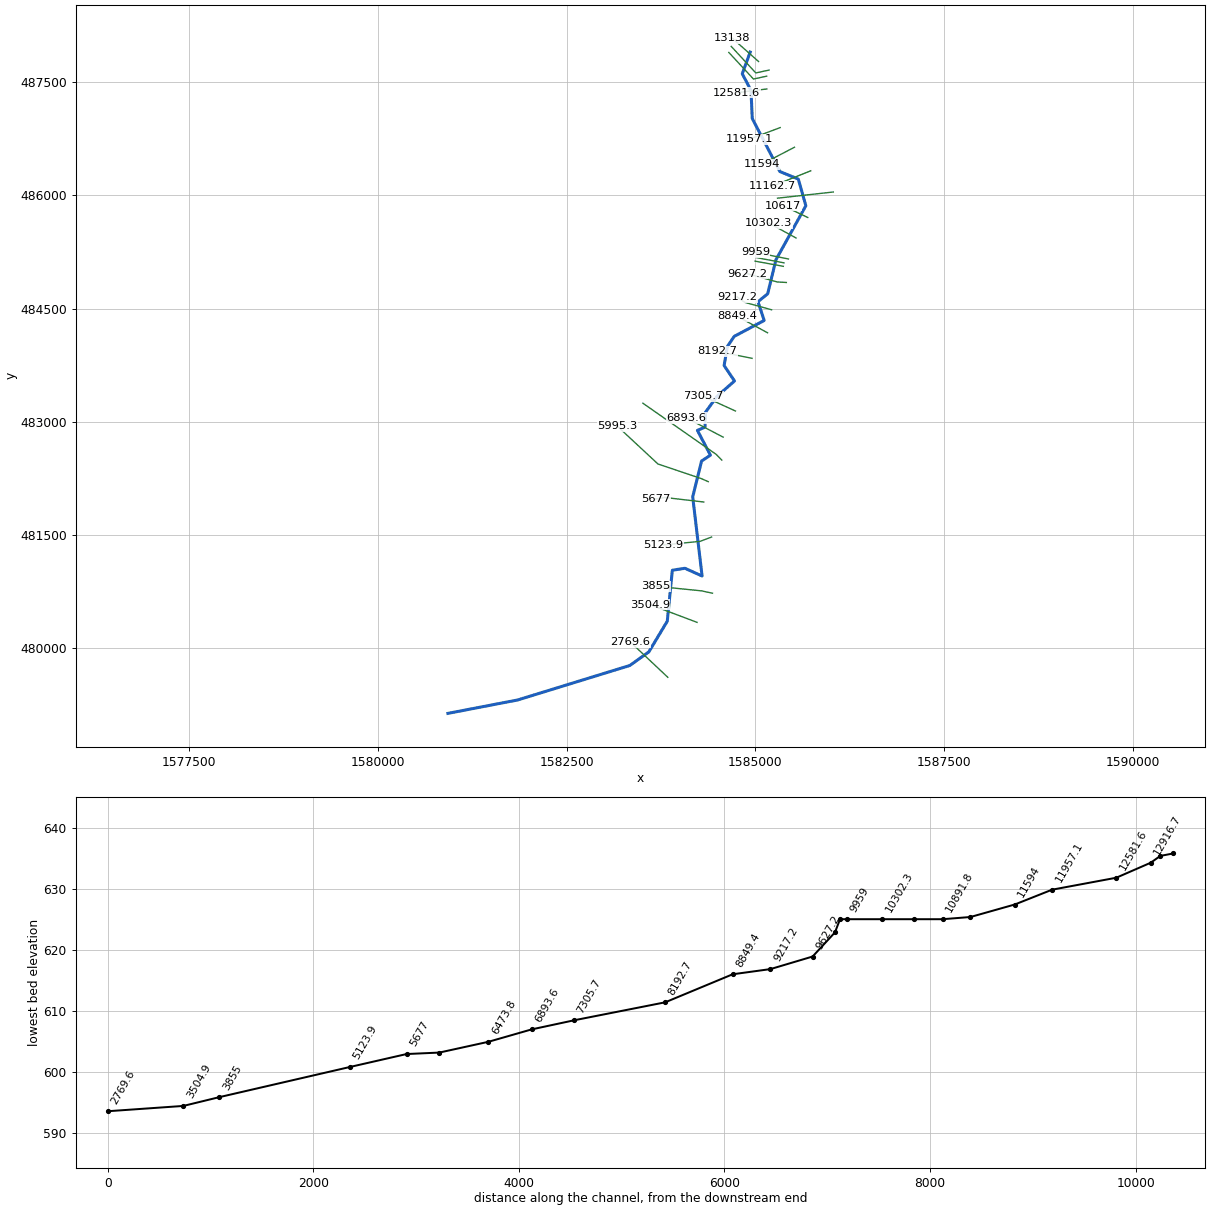
--- LongBr.prj (project) ---

Proj Title=LongBr
Current Plan=p01
Geom File=g01
Flow File=f01
Plan File=p01
DSS Export Rating Curves=0
DSS Export Rating Curve Sorted=0
DSS Export Volume Flow Curves=0
DXF OffsetX=0
DXF OffsetY=0
DXF ScaleX=0
DXF ScaleY=0

--- LongBr.p01 (plan) ---

Plan Title=Floodplain
Program Version=4.00
Geom File=g01
Flow File=f01
K Sum by GR=0
Std Step Tol=0.01
Critical Tol=0.01
Num of Std Step Trials=20
Max Error Tol=0.3
Flow Tol Ratio=0.001
Split Flow NTrial=30
Split Flow Tol=0.02
Split Flow Ratio=0.02
Log Output Level=0
Friction Slope Method=1
Unsteady Friction Slope Method=2
Unsteady Bridges Friction Slope Method=1
Global Log Level=0
CheckData=False
Run HTab=0
Run UNet=0
Run PostProcess=0
UNET Theta=0
UNET Theta Warmup=0
UNET ZTol=0
UNET ZSATol=0
UNET MxIter=0
UNET MaxInSteps=0
UNET DtIC=0
UNET DtMin=0
UNET MaxCRTS=0
UNET WFStab=0
UNET SFStab=0
UNET WFX=0
UNET SFX=0
UNET DSS MLevel=0
UNET DZMax Abort=0
UNET Convert EG Bridges=0
UNET Use Existing IB Tables=0
UNET Froude Limit=0
UNET Froude Power=0
Write IC File=0
Echo Input=False
Echo Output=False
Write Detailed=0

--- LongBr.f01 (steady flow) ---

Flow Title=NFF Regression Equation
Program Version=4.10
Number of Profiles= 1
Profile Names=P100yr
River Rch & RM=LongBr,Main            ,13138
    1043
River Rch & RM=LongBr,Main            ,11957.1
    1076
River Rch & RM=LongBr,Main            ,11594
    1083
River Rch & RM=LongBr,Main            ,11162.7
    1103
River Rch & RM=LongBr,Main            ,9627.2
    1168
River Rch & RM=LongBr,Main            ,9217.2
    1177
River Rch & RM=LongBr,Main            ,8192.7
    1196
River Rch & RM=LongBr,Main            ,7305.7
    1217
River Rch & RM=LongBr,Main            ,6473.8
    1228
River Rch & RM=LongBr,Main            ,5995.3
    1254
River Rch & RM=LongBr,Main            ,5677
    1542
River Rch & RM=LongBr,Main            ,5123.9
    1548
River Rch & RM=LongBr,Main            ,3855
    1556
River Rch & RM=LongBr,Main            ,3504.9
    1565
Boundary for River Rch & Prof#=LongBr,Main            , 1
Up Type= 0
Dn Type= 3
Dn Slope=0.0012
DSS Import GetInterval= 0
DSS Import GetPeak= 0
DSS Import FillOption= 0

--- LongBr.g01 (geometry) ---

Geom Title=USGS 10m DEM
Program Version=4.10

River Reach=LongBr          ,Main
Reach XY= 30
     1584930.459      487898.769     1584824.919      487611.696
     1584940.804      487390.341     1584957.731      487017.946
     1585322.532       486316.34     1585567.757      486215.428
     1585667.584      485862.781     1585271.533      485146.635
     1585161.941      484696.331     1585033.903      484591.079
     1585115.283      484342.598     1584719.233      484132.095
     1584628.087      483998.631     1584584.684       483745.81
     1584722.488      483540.732     1584493.539      483339.994
     1584336.693      483125.428     1584331.863      482928.753
     1584230.952      482886.435     1584403.478      482557.659
      1584286.19      482480.414     1584168.669      482005.576
     1584292.801      480956.965      1584065.37      481059.395
     1583898.703      481033.354     1583831.776      480358.571
     1583587.636       479951.67       1583335.9      479771.548
      1581850.44      479314.734     1580925.218       479136.96

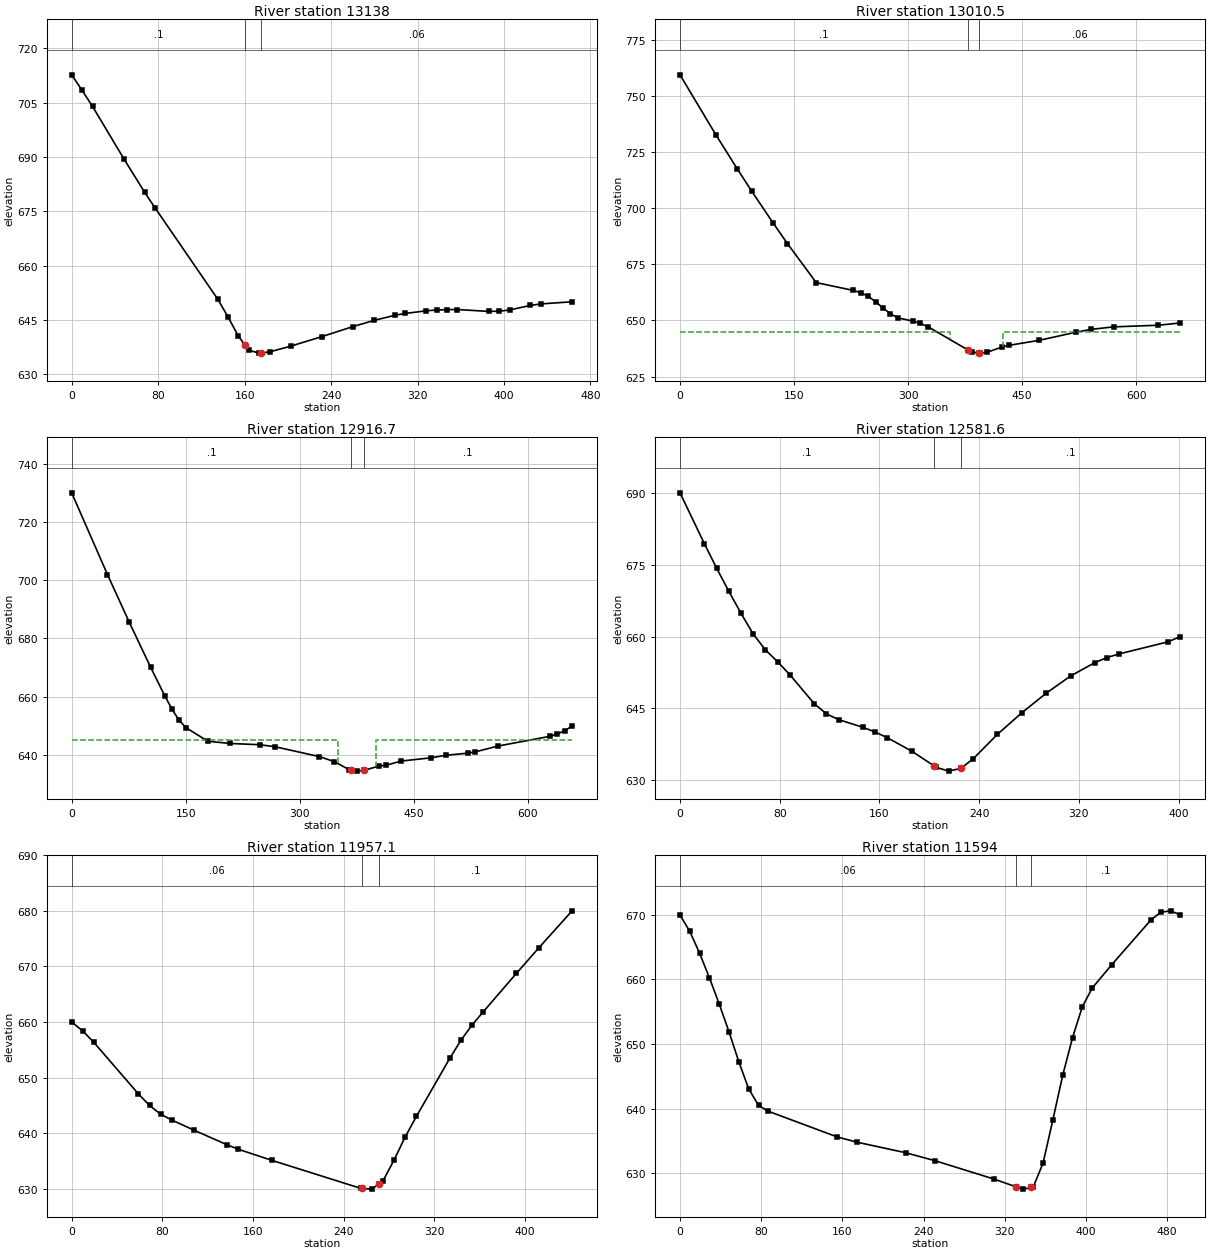
Type RM Length L Ch R = 1 ,13138   ,133.5,127.5,119.6
XS GIS Cut Line= 2
     1585041.048      487773.322     1584694.694      488080.613
#Sta/Elev= 30
       0  712.64     9.6  708.38    19.3  703.92    48.2  689.52    67.5  680.25
    77.2  675.92     135  650.83   144.7  645.85   154.3  640.54   160.2  638.19
     164  636.67   173.6  635.89   175.2  635.95   183.3  636.24   202.6  637.81
   231.5  640.44   260.4  643.23   279.7  644.91     299  646.32   308.7  646.84
     328  647.55   337.6  647.78   347.3  647.88   356.9  647.91   385.8   647.4
   395.5  647.45   405.1  647.79   424.4  649.04   434.1  649.46     463  650.05
#Mann= 3 , 0 , 0
       0      .1       0   160.2    .045       0   175.2     .06       0
Bank Sta=160.2,175.2
XS Rating Curve= 0 ,0
Exp/Cntr=0.3,0.1

Type RM Length L Ch R = 1 ,13010.5 ,90.4,93.9,99.1
XS GIS Cut Line= 3
     1585179.753      487659.868      1585004.59       487622.28
     1584679.069      487973.842
#Sta/Elev= 30
       0  759.32    47.1  732.69    75.4  717.44    94.3  707.56   122.6  693.35
   141.4  684.21   179.2  666.86     228  663.39   237.8  662.36   247.6  660.74
   257.4  658.33   267.2   655.5   276.9  652.99   286.7  651.15   306.3  649.75
     316   648.7   325.8  647.31   378.6  636.93   384.5  635.97   393.6  635.52
   394.3  635.48     404  635.86   423.6  638.22   433.4  638.98   472.5  641.17
   521.4  644.83   540.9  646.05   570.3  647.16   628.9  647.89   658.3   648.9
#Mann= 3 , 0 , 0
       0      .1       0   378.6    .045       0   393.6     .06       0
#XS Ineff= 2 , 0
       0     355     645     425       0     645
Permanent Ineff=
       F       F
Bank Sta=378.6,393.6
XS Rating Curve= 0 ,0
Exp/Cntr=0.3,0.1

Type RM Length L Ch R = 1 ,12916.7 ,313.2,335,356.6
XS GIS Cut Line= 3
     1585148.503      487579.139      1584973.34      487541.551
     1584647.819      487893.113
#Sta/Elev= 30
       0     730    47.1   701.9    75.4  685.73   103.7  670.13   122.6  660.16
     132  655.64   141.4  651.78   150.9   649.2   179.2  644.62   208.5  643.87
   247.6  643.43   267.2  642.76   325.8  639.36   345.4  637.64   364.9  634.88
   367.9  634.72   374.7  634.36   384.5  634.61     404   636.1   413.8   636.4
   433.4  637.82   472.5  638.93     492   639.8   521.4  640.54   531.2  640.99
   560.5  642.96   628.9  646.31   638.7  647.08   648.5  648.26   658.3  649.85
#Mann= 3 , 0 , 0
       0      .1       0   367.9    .045       0   384.5      .1       0
#XS Ineff= 2 , 0
       0     350     645     400       0     645
Permanent Ineff=
       F       F
Bank Sta=367.9,384.5
XS Rating Curve= 0 ,0
Exp/Cntr=0.3,0.1

Type RM Length L Ch R = 1 ,12581.6 ,619.2,624.5,629.7
XS GIS Cut Line= 2
     1585150.759      487409.791     1584752.425      487360.578
#Sta/Elev= 30
       0     690    19.6  679.36    29.4  674.27    39.2  669.43      49  664.82
    58.7  660.54    68.5  657.22    78.3  654.74    88.1  652.03   107.7  645.98
   117.5  643.85   127.3  642.65   146.8  641.04   156.6  640.06   166.4  638.86
     186  636.05   203.7  633.01   205.6  632.69   215.4   631.9   225.2  632.47
   234.9  634.39   254.5  639.55   274.1  644.06   293.7  648.16   313.3  651.76
   332.8  654.56   342.6  655.62   352.4  656.38   391.6   658.9   401.4     660
#Mann= 3 , 0 , 0
       0      .1       0   203.7    .045       0   225.2      .1       0
Bank Sta=203.7,225.2
XS Rating Curve= 0 ,0
Exp/Cntr=0.3,0.1

Type RM Length L Ch R = 1 ,11957.1 ,360.1,363.1,365.7
XS GIS Cut Line= 2
      1585327.53      486897.981      1584914.23      486742.448
#Sta/Elev= 26
       0     660     9.8  658.38    19.6  656.33    58.9  647.06    68.7  644.99
    78.5  643.41    88.3  642.37     108  640.54   137.4  637.89   147.2   637.1
   176.6  635.12   255.1  630.08   256.4  630.06     265  629.94   271.4  630.93
   274.8  631.45   284.6  635.22   294.4  639.37   304.2  643.02   333.6  653.45
   343.5  656.71   353.3  659.46   363.1  661.81   392.5  668.76   412.2  673.33
   441.6     680
#Mann= 3 , 0 , 0
       0     .06       0   256.4    .045       0   271.4      .1       0
Bank Sta=256.4,271.4
XS Rating Curve= 0 ,0
Exp/Cntr=0.3,0.1

Type RM Length L Ch R = 1 ,11594   ,434.1,431.3,427.5
XS GIS Cut Line= 2
     1585516.991       486637.76     1585079.605      486410.003
#Sta/Elev= 30
       0  669.99     9.7  667.44    19.3  664.08      29  660.26    38.7  656.18
    48.4  651.84      58  647.23    67.7  643.05    77.4  640.49      87  639.58
   154.7  635.61     174   634.8   222.4  633.15   251.4  631.91   309.4  629.07
   331.3  627.86   338.4  627.51   346.3  627.77   348.1  627.83   357.8  631.57
   367.4  638.22   377.1  645.13   386.8  650.98   396.4  655.74   406.1  658.65
   425.4  662.28   464.1  669.23   473.8  670.43   483.5  670.64   493.1     670
#Mann= 3 , 0 , 0
       0     .06       0   331.3    .045       0   346.3      .1       0
Bank Sta=331.3,346.3
XS Rating Curve= 0 ,0
Exp/Cntr=0.3,0.1

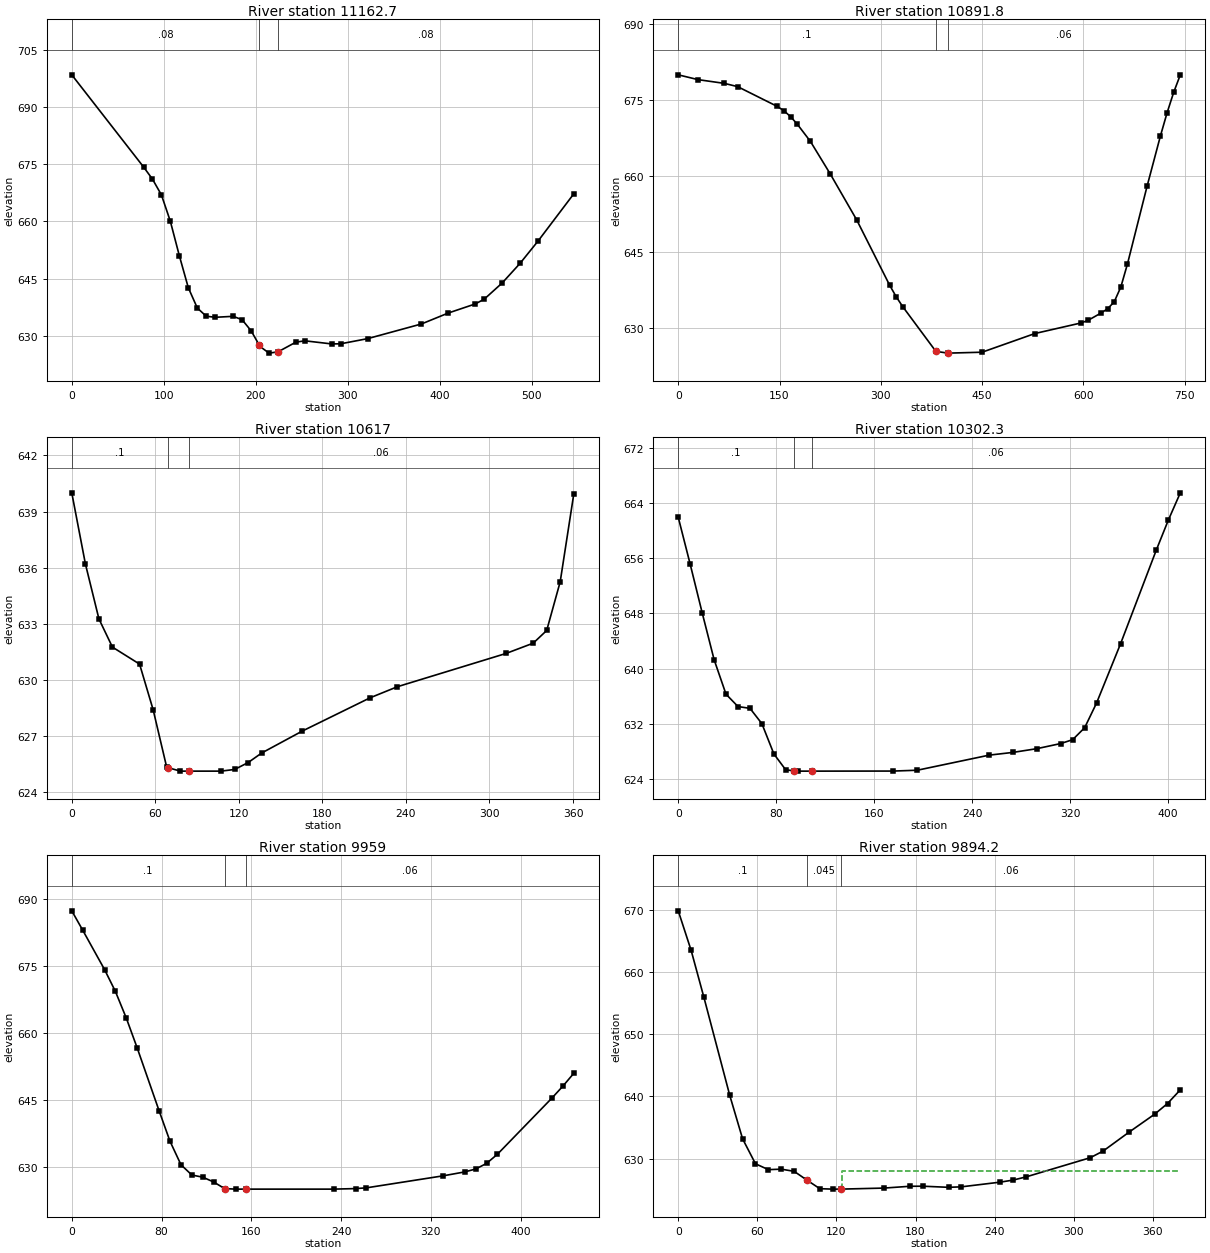
Type RM Length L Ch R = 1 ,11162.7 ,276.8,270.9,265.6
XS GIS Cut Line= 2
     1585732.268        486325.5      1585225.52      486122.453
#Sta/Elev= 30
       0  698.45      78   674.3    87.7  671.11    97.5  666.95   107.2  660.02
     117  650.97   126.7  642.62   136.5  637.29   146.2  635.14     156  634.86
   175.5  635.11   185.2  634.22     195  631.32   203.8  627.58   204.7   627.2
   214.5  625.46   224.2  625.79   243.7  628.34   253.5  628.69   282.7  627.87
   292.4  627.91   321.7  629.26   380.2  633.11   409.4  635.98   438.7  638.36
   448.4   639.6   467.9  643.84   487.4     649   506.9  654.83   545.9  667.26
#Mann= 3 , 0 , 0
       0     .08       0   203.8    .045       0   224.2     .08       0
Bank Sta=203.8,224.2
XS Rating Curve= 0 ,0
Exp/Cntr=0.3,0.1

Type RM Length L Ch R = 1 ,10891.8 ,287.3,274.8,262.3
XS GIS Cut Line= 2
     1586031.328      486044.684     1585292.276      485962.943
#Sta/Elev= 30
       0     680    29.4  679.05    68.5  678.31      88  677.67   146.8  673.76
   156.5  672.92   166.3  671.76   176.1   670.3   195.7  666.88     225  660.48
   264.2  651.41   313.1   638.5   322.9   636.2   332.6  634.25   381.6  625.44
   399.8   625.1     450  625.28   528.3  628.97   596.8  631.06   606.6  631.54
   626.2  633.01   635.9  633.85   645.7  635.22   655.5  638.14   665.3  642.68
   694.6  658.14   714.2  667.97     724  672.51   733.8  676.55   743.6     680
#Mann= 3 , 0 , 0
       0      .1       0   381.6    .045       0   399.8     .06       0
Bank Sta=381.6,399.8
XS Rating Curve= 0 ,0
Exp/Cntr=0.3,0.1

Type RM Length L Ch R = 1 ,10617   ,315.9,314.7,313.7
XS GIS Cut Line= 2
     1585693.041      485707.038     1585367.475      485862.081
#Sta/Elev= 22
       0     640     9.8  636.19    19.5  633.25    29.2  631.74    48.7  630.83
    58.5  628.37    68.2   625.3    68.9  625.29      78   625.1    83.9   625.1
   107.2   625.1     117  625.19   126.7  625.56   136.4  626.07   165.7  627.25
   214.4  629.03   233.9  629.62   311.9   631.4   331.4  631.95   341.1  632.63
   350.8  635.24   360.6  639.96
#Mann= 3 , 0 , 0
       0      .1       0    68.9    .045       0    83.9     .06       0
Bank Sta=68.9,83.9
XS Rating Curve= 0 ,0
Exp/Cntr=0.3,0.1

Type RM Length L Ch R = 1 ,10302.3 ,336.8,343.3,349.6
XS GIS Cut Line= 2
     1585538.155      485435.271     1585178.532      485632.118
#Sta/Elev= 26
       0  661.98     9.8  655.13    19.5  648.14    29.3  641.29      39  636.28
    48.8  634.48    58.6  634.22    68.3     632    78.1   627.6    87.8  625.28
    94.2  625.16    97.6   625.1   109.2   625.1   175.7  625.11   195.2  625.23
   253.8  627.42   273.3  627.82   292.8  628.36   312.4  629.11   322.1  629.67
   331.9  631.41   341.6  634.99   361.2   643.6   390.4  657.22   400.2  661.56
     410  665.53
#Mann= 3 , 0 , 0
       0      .1       0    94.2    .045       0   109.2     .06       0
Bank Sta=94.2,109.2
XS Rating Curve= 0 ,0
Exp/Cntr=0.3,0.1

Type RM Length L Ch R = 1 ,9959    ,64.7,64.8,64.9
XS GIS Cut Line= 2
      1585437.02      485157.267     1584998.405      485245.497
#Sta/Elev= 26
       0  687.25     9.7  682.95    29.2  674.14    38.9  669.24    48.6  663.29
    58.4  656.56    77.8  642.61    87.5  635.81    97.3  630.55     107  628.25
   116.7  627.77   126.4   626.7   136.2  625.22   145.9   625.1   155.5   625.1
   233.4   625.1   252.9  625.22   262.6  625.39   330.7  628.06   350.1  628.94
   359.9  629.59   369.6  630.84   379.3  632.89     428  645.47   437.7  648.12
   447.4  650.98
#Mann= 3 , 0 , 0
       0      .1       0   136.2    .045       0   155.5     .06       0
Bank Sta=136.2,155.5
XS Rating Curve= 0 ,0
Exp/Cntr=0.3,0.1

Type RM Length L Ch R = 1 ,9894.2  ,49.7,49.5,49.8
XS GIS Cut Line= 2
     1585378.691      485105.965     1585004.559      485177.145
#Sta/Elev= 27
       0  669.83     9.8  663.46    19.5   655.9    39.1  640.15    48.8  633.19
    58.6  629.17    68.4  628.23    78.1  628.31    87.9  627.96    97.6  626.55
   107.4  625.17   117.2   625.1   123.1   625.1   156.2  625.27   175.8  625.56
   185.5  625.57   205.1  625.39   214.8  625.47   244.1  626.22   253.9  626.55
   263.7  627.06   312.5  630.15   322.2  631.21   341.8  634.24   361.3  637.14
   371.1  638.86   380.8  641.06
#Mann= 3 , 0 , 0
       0      .1       0    97.6    .045       0   123.1     .06       0
#XS Ineff= 2 , 0
       0      86     628     124       0     628
Permanent Ineff=
       F       F
Bank Sta=97.6,123.1
XS Rating Curve= 0 ,0
Exp/Cntr=0.3,0.1

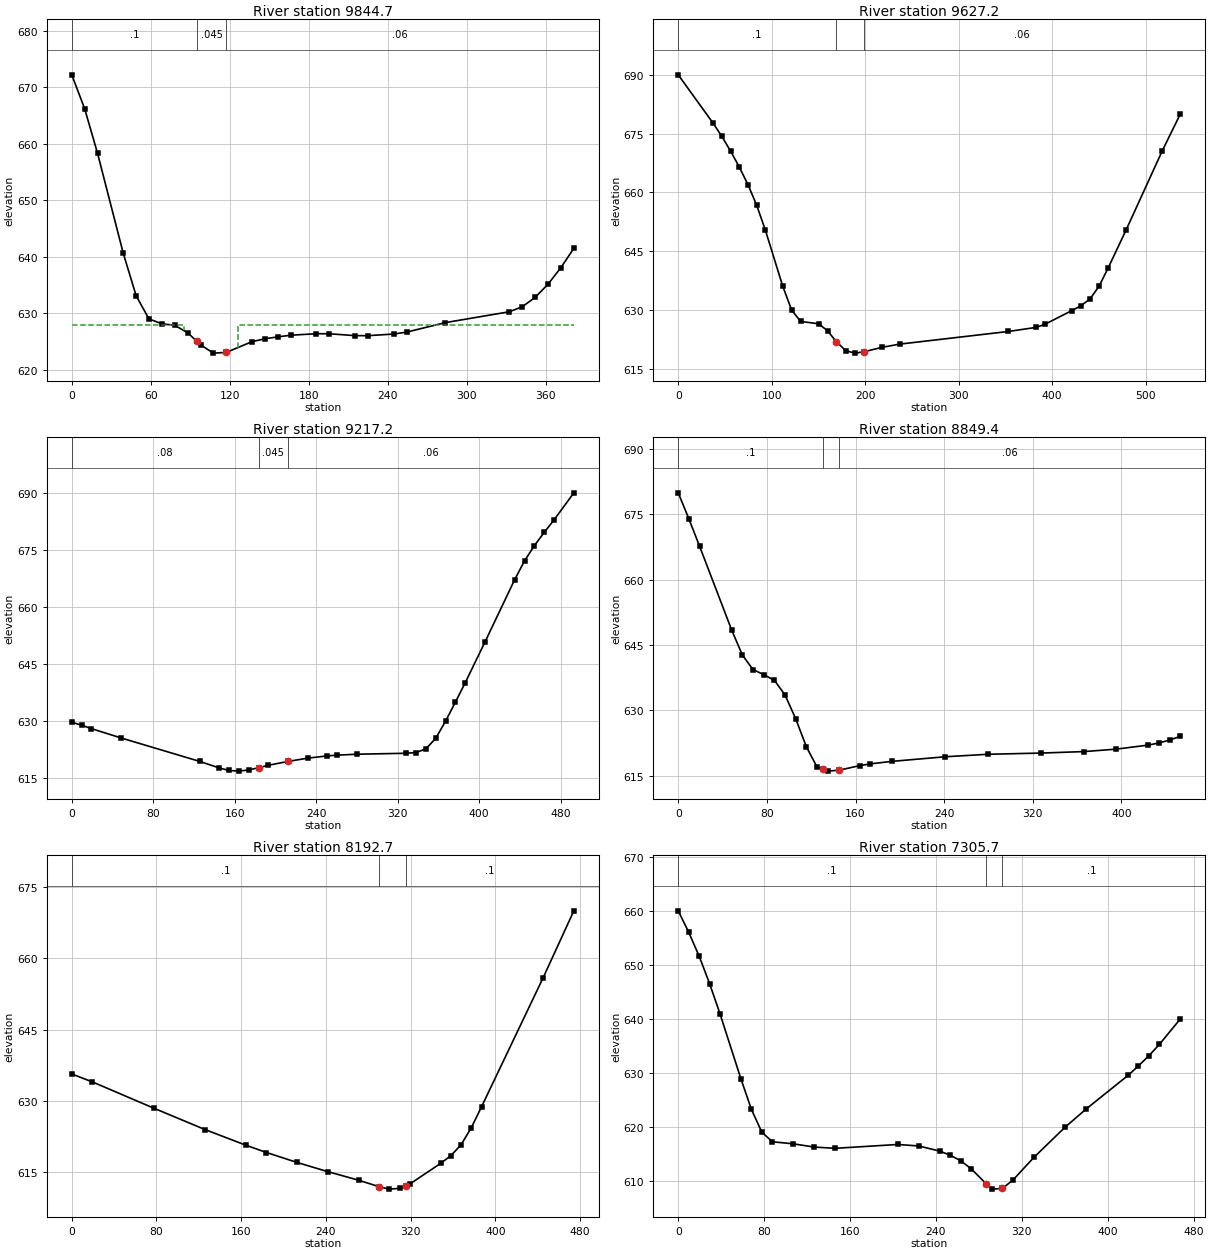
Type RM Length L Ch R = 1 ,9844.7  ,218.9,217.5,214.9
XS GIS Cut Line= 2
     1585369.316      485060.131     1584994.316      485128.708
#Sta/Elev= 30
       0  672.24     9.8  666.23    19.6  658.31    39.1  640.62    48.9  633.09
    58.6     629    68.4  628.14    78.2  627.86      88  626.55    94.9  625.04
    97.8  624.41   107.5  622.94   117.3  623.06   136.8  624.97   146.6  625.48
   156.4  625.82   166.2  626.11   185.7  626.38   195.5  626.37     215  626.04
   224.8  626.03   244.4  626.32   254.2  626.66   283.5  628.34   332.3  630.27
   342.1  631.17   351.9  632.83   361.7  635.18   371.4   638.1   381.2  641.51
#Mann= 3 , 0 , 0
       0      .1       0    94.9    .045       0   117.3     .06       0
#XS Ineff= 2 , 0
       0      85     628     126       0     628
Permanent Ineff=
       F       F
Bank Sta=94.9,117.3
XS Rating Curve= 0 ,0
Exp/Cntr=0.3,0.1

Type RM Length L Ch R = 1 ,9627.2  ,410.3,410,409.4
XS GIS Cut Line= 3
     1585409.405      484845.895     1585288.456      484852.899
     1584887.715      484963.968
#Sta/Elev= 30
       0     690    37.3  677.66    46.6  674.29    55.9  670.58    65.2  666.51
    74.6  661.97    83.9  656.71    93.2  650.36   111.8  636.03   121.2  630.01
   130.8  627.08   150.2  626.46   159.8  624.66     169  621.92   179.2   619.6
   188.8  618.98   198.5  619.31   217.9  620.46   237.2  621.29   353.2  624.51
   382.3  625.53   391.9   626.3     421  629.84   430.6  631.07   440.3  632.77
     450  636.02   459.6   640.6     479   650.4   517.7  670.61     537     680
#Mann= 3 , 0 , 0
       0      .1       0     169    .045       0   198.5     .06       0
Bank Sta=169,198.5
XS Rating Curve= 0 ,0
Exp/Cntr=0.3,0.1

Type RM Length L Ch R = 1 ,9217.2  ,373.6,367.8,361.9
XS GIS Cut Line= 3
     1585213.761      484484.437     1584860.071      484581.994
     1584756.549      484653.891
#Sta/Elev= 30
       0  629.75     9.7  628.98    19.3  628.08    48.3  625.64   125.5  619.48
   144.8  617.76   154.5  617.09   164.1  616.92   173.8  617.23   183.4  617.81
   193.1  618.46   212.1  619.46   231.7  620.33     251  620.92   260.7  621.12
     280  621.36   328.3  621.61   337.9   621.8   347.6  622.76   357.2   625.5
   366.9     630   376.6  635.01   386.3  640.16   405.7  650.86   434.8   667.2
   444.5  672.14   454.2  676.16   463.8   679.6   473.6  682.94   492.9     690
#Mann= 3 , 0 , 0
       0     .08       0   183.4    .045       0   212.1     .06       0
Bank Sta=183.4,212.1
XS Rating Curve= 0 ,0
Exp/Cntr=0.3,0.1

Type RM Length L Ch R = 1 ,8849.4  ,648.4,656.8,664.9
XS GIS Cut Line= 2
     1585160.482      484179.315     1584762.402      484395.717
#Sta/Elev= 27
       0  679.97     9.6     674    19.3  667.68    48.2  648.48    57.8  642.76
    67.5  639.38    77.1  638.23    86.8  636.92    96.4  633.54     106   628.1
   115.7  621.62   125.3     617   130.3  616.52     135  616.07   145.3  616.29
   163.9  617.34   173.5  617.74   192.8  618.31     241  619.37   279.6  619.94
   327.8  620.22   366.3  620.56   395.3  621.12   424.2  622.05   433.8  622.53
   443.5  623.21   453.1  624.05
#Mann= 3 , 0 , 0
       0      .1       0   130.3    .045       0   145.3     .06       0
Bank Sta=130.3,145.3
XS Rating Curve= 0 ,0
Exp/Cntr=0.3,0.1

Type RM Length L Ch R = 1 ,8192.7  ,893.4,886.9,873.7
XS GIS Cut Line= 2
     1584955.111       483841.03     1584490.173      483934.271
#Sta/Elev= 21
       0  635.68    19.4  634.02    77.4   628.5   125.8     624   164.5   620.7
   183.9  619.17   212.9  617.07   241.9  615.14     271  613.34   290.3  611.98
     300  611.47   309.7  611.63   315.3  612.17   319.4  612.56   348.4  616.89
   358.1  618.51   367.7  620.81   377.4   624.4   387.1  628.82   445.2  655.92
   474.2  669.99
#Mann= 3 , 0 , 0
       0      .1       0   290.3    .045       0   315.3      .1       0
Bank Sta=290.3,315.3
XS Rating Curve= 0 ,0
Exp/Cntr=0.3,0.1

Type RM Length L Ch R = 1 ,7305.7  ,413.5,412.2,411.5
XS GIS Cut Line= 2
     1584735.118      483142.958     1584309.698      483337.188
#Sta/Elev= 30
       0     660     9.7  656.06    19.5  651.61    29.2  646.54      39  640.89
    58.5  628.85    68.2  623.25    77.9  619.05    87.7  617.28   107.2   616.9
   126.7   616.3   146.1  616.07   204.6  616.78   224.1   616.5   243.6  615.55
   253.3   614.8   263.1  613.77   272.8   612.3   286.9   609.5   292.3  608.52
   301.9  608.64   311.8   610.2   331.3  614.39   360.5     620     380  623.34
     419  629.56   428.7  631.31   438.4  633.19   448.2  635.29   467.7     640
#Mann= 3 , 0 , 0
       0      .1       0   286.9    .045       0   301.9      .1       0
Bank Sta=286.9,301.9
XS Rating Curve= 0 ,0
Exp/Cntr=0.3,0.1

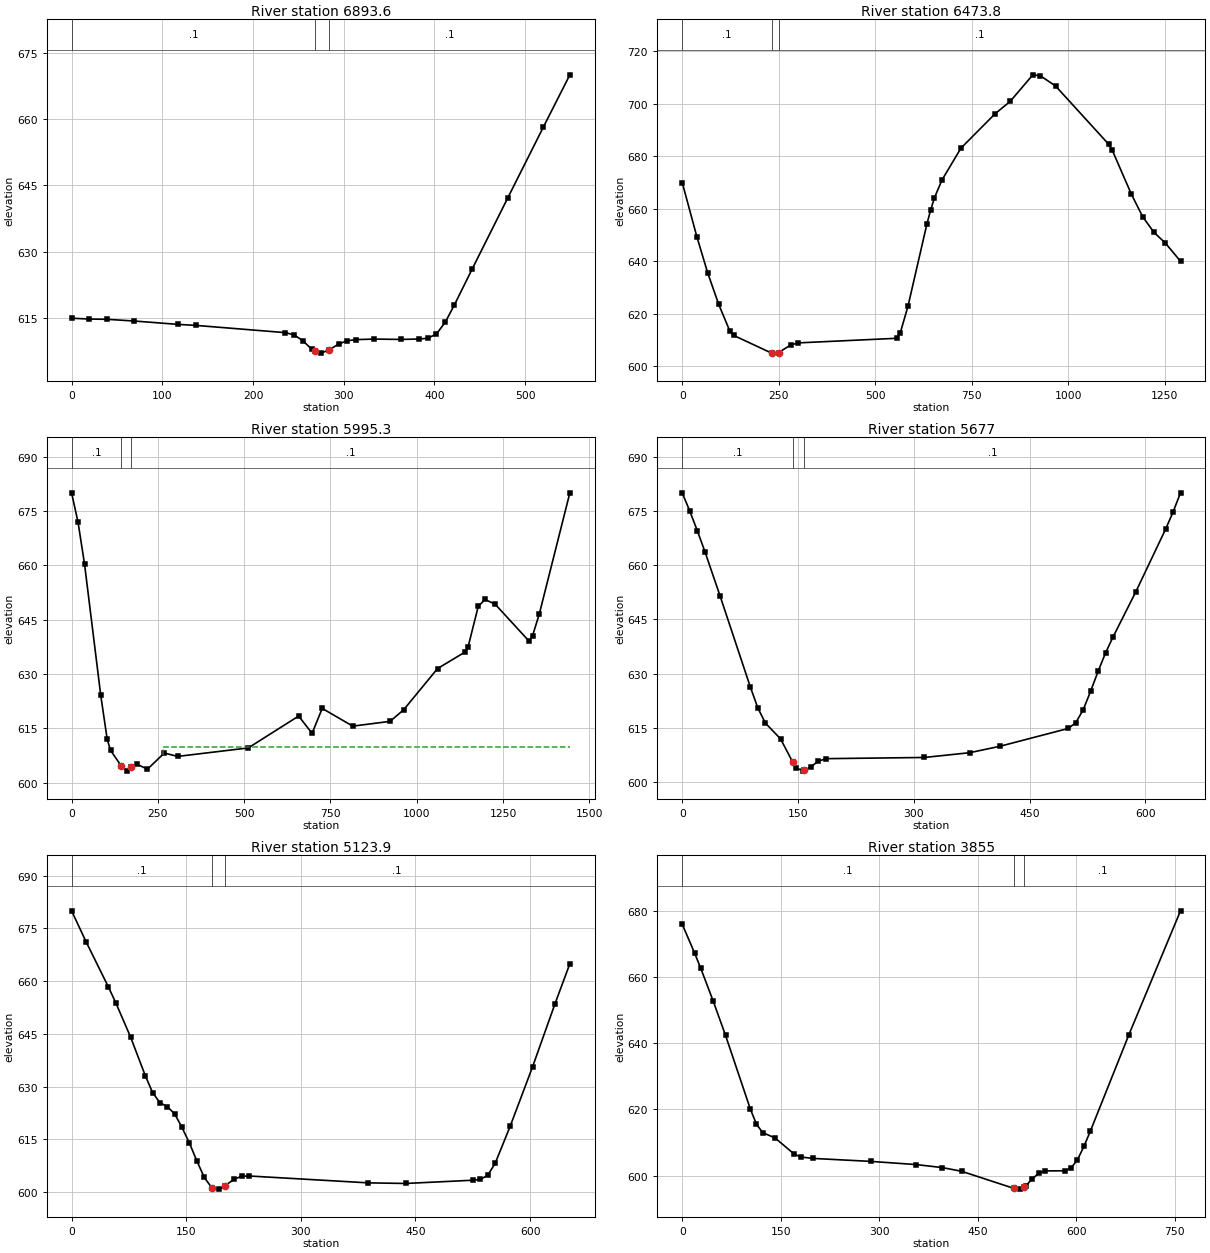
Type RM Length L Ch R = 1 ,6893.6  ,433,419.8,408
XS GIS Cut Line= 2
     1584572.298      482796.759     1584085.513      483051.256
#Sta/Elev= 27
       0  614.93    19.6  614.74    39.2  614.68    68.7   614.3   117.7  613.53
   137.3   613.3   235.4  611.67   245.2  611.17     255  609.83   264.8   607.9
   268.7  607.55   274.6  607.03   283.7  607.71   294.3  609.09   304.1  609.84
   313.9  610.09   333.5  610.21   362.9  610.13   382.6  610.22   392.4  610.38
   402.2  611.35     412  614.05   421.8  617.85   441.4  625.98   480.6  642.05
   519.9   658.1   549.3     670
#Mann= 3 , 0 , 0
       0      .1       0   268.7    .045       0   283.7      .1       0
Bank Sta=268.7,283.7
XS Rating Curve= 0 ,0
Exp/Cntr=0.3,0.1

Type RM Length L Ch R = 1 ,6473.8  ,459,478.5,494.1
XS GIS Cut Line= 3
     1584553.876      482492.618      1584481.35      482567.281
     1583508.516      483246.413
#Sta/Elev= 30
       0     670    37.8   649.4    66.2  635.46    94.6  623.54   123.7  613.26
   133.5  611.73   231.6     605   249.6  605.22   280.6  608.07   300.2   608.9
   555.1  610.65   564.9  612.82   584.6  622.81   633.6  654.13   643.4  659.51
   653.2  664.17   672.8  670.97   721.8  683.07   810.1  696.16   849.3  700.88
   908.1  711.02   927.7  710.65     967  706.75  1104.2  684.62    1114  682.22
  1163.1  665.59  1192.5  656.98  1221.9  650.98  1251.3  646.93  1290.5     640
#Mann= 3 , 0 , 0
       0      .1       0   231.6    .045       0   249.6      .1       0
Bank Sta=231.6,249.6
XS Rating Curve= 0 ,0
Exp/Cntr=0.3,0.1

Type RM Length L Ch R = 1 ,5995.3  ,313.6,318.3,323
XS GIS Cut Line= 4
     1584374.736      482206.899     1584280.311      482248.317
     1583708.552      482441.034     1583168.708      482942.749
#Sta/Elev= 30
       0     680    18.8  671.84    37.5  660.36    84.4   624.2   103.1  612.06
   112.8  608.97   144.6  604.56   161.5  603.23   171.2  604.35   190.7  605.06
   219.9  603.77   268.6  608.22   307.5  607.29   511.8  609.63   657.8  618.42
   696.7  613.66   726.1  620.53   814.6  615.64   922.7  616.96     962  620.15
  1060.2  631.52  1138.8  636.02  1148.7   637.5  1178.1  648.69  1197.8  650.58
  1227.3  649.25  1325.5  639.07  1335.4  640.57    1355  646.59  1443.5     680
#Mann= 3 , 0 , 0
       0      .1       0   144.6    .045       0   171.2      .1       0
#XS Ineff= 2 , 0
                          263.66          609.93
Permanent Ineff=
       F       F
Bank Sta=144.6,171.2
XS Rating Curve= 0 ,0
Exp/Cntr=0.3,0.1

Type RM Length L Ch R = 1 ,5677    ,548.4,553.2,557.6
XS GIS Cut Line= 3
     1584315.125      481937.361     1583799.046       481997.45
     1583674.712      481976.731
#Sta/Elev= 30
       0     680     9.8  674.94    19.6   669.5    29.4  663.74      49  651.49
    88.2  626.31      98  620.46   107.8  616.27   127.4  611.92   143.4  605.39
     147  603.98   156.8  602.99   158.4  603.19   166.6  604.21   176.5  605.74
   186.3  606.44   313.7  606.77   372.5  608.09   411.7  609.87     500  614.79
   509.8  616.35   519.6     620   529.3  625.19     539  630.69   548.6  635.77
   558.4   640.2   587.4  652.48   626.2   669.9   635.9  674.67   645.6     680
#Mann= 3 , 0 , 0
       0      .1       0   143.4    .045       0   158.4      .1       0
Bank Sta=143.4,158.4
XS Rating Curve= 0 ,0
Exp/Cntr=0.3,0.1

Type RM Length L Ch R = 1 ,5123.9  ,1256.2,1268.9,1270.5
XS GIS Cut Line= 3
     1584418.886      481473.491     1584265.584      481415.827
     1583779.733      481368.117
#Sta/Elev= 30
       0  679.99    19.3  671.05    48.2  658.33    57.8  653.86    77.1  644.15
    96.4  633.16     106  628.31   115.6  625.43   125.2  624.33   134.9  622.25
   144.5  618.39   154.2  613.95   163.8  608.94   173.6   604.2   183.3   601.3
   193.1  600.86   200.1  601.71   212.6  603.67   222.4  604.52   232.1   604.6
   388.4  602.64   437.2  602.47     525  603.39   534.8  603.62   544.6   604.8
   554.3  608.22   573.9  618.74   603.2  635.64   632.4  653.47     652  664.96
#Mann= 3 , 0 , 0
       0      .1       0   183.3    .045       0   200.1      .1       0
Bank Sta=183.3,200.1
XS Rating Curve= 0 ,0
Exp/Cntr=0.3,0.1

Type RM Length L Ch R = 1 ,3855    ,353.3,350.1,343.9
XS GIS Cut Line= 3
     1584430.774      480729.229     1584283.205      480760.479
     1583678.234      480821.422
#Sta/Elev= 30
       0  675.96    18.9  667.22    28.3   662.6    47.1  652.78      66  642.36
   103.7  620.14   113.1  615.54   122.6  612.98   141.4  611.38   170.5  606.51
   180.3  605.63   199.9  605.19   288.1  604.29   356.8  603.33     396  602.43
   425.4  601.32   505.7  596.11   513.7  595.92   520.7  596.69   523.5     597
   533.3  599.03   543.1  600.74   552.9  601.43   582.4  601.46   592.2   602.3
     602  604.81   611.8  608.82   621.6  613.44   680.4  642.62   758.9     680
#Mann= 3 , 0 , 0
       0      .1       0   505.7    .045       0   520.7      .1       0
Bank Sta=505.7,520.7
XS Rating Curve= 0 ,0
Exp/Cntr=0.3,0.1

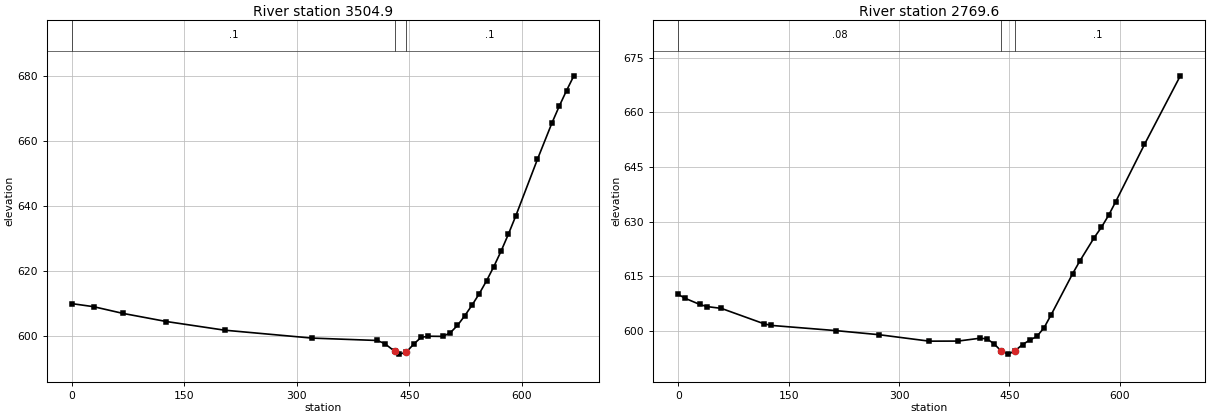
Type RM Length L Ch R = 1 ,3504.9  ,742.8,735.3,726.5
XS GIS Cut Line= 2
     1584226.335      480342.876     1583600.108      480579.096
#Sta/Elev= 30
       0     610    29.1  609.06    67.9  607.01   126.1   604.5   203.7  601.84
   320.1  599.41   407.4  598.67   417.1  597.72   430.6  595.34   436.5  594.48
   445.6  595.01   455.9  597.57   465.6  599.62   475.3  599.98   494.7  599.93
   504.4     601   514.1  603.28   523.8  606.25   533.5   609.5   543.2  613.04
   552.9  617.01   562.6  621.37   572.3  626.14     582  631.31   591.7  636.84
   620.8  654.36   640.2  665.57   649.9  670.71   659.6  675.49   669.3     680
#Mann= 3 , 0 , 0
       0      .1       0   430.6    .045       0   445.6      .1       0
Bank Sta=430.6,445.6
XS Rating Curve= 0 ,0
Exp/Cntr=0.3,0.1

Type RM Length L Ch R = 1 ,2769.6  ,2788,2769.6,2752.8
XS GIS Cut Line= 2
     1583839.096      479614.531     1583342.305      480082.148
#Sta/Elev= 30
       0     610     9.8   608.9    29.2  607.25      39  606.66    58.5  606.17
     117  601.91   126.7  601.49   214.4  600.06   272.9  598.94   341.1  597.17
   380.1  597.19   409.4  597.96   419.1  597.84   428.8   596.5   438.6  594.52
   448.3  593.61     457  594.43   467.8  596.23   477.6  597.46   487.3  598.47
   497.1  600.86   506.8  604.45     536  615.73   545.8  619.22   565.3  625.62
     575  628.42   584.8  631.72   594.5  635.49   633.5  651.17   682.2     670
#Mann= 3 , 0 , 0
       0     .08       0   438.6    .045       0     457      .1       0
Bank Sta=438.6,457
XS Rating Curve= 0 ,0
Exp/Cntr=0.3,0.1

Chan Stop Cuts=-1
Use User Specified Reach Order=0
Composite Channel Slope=5